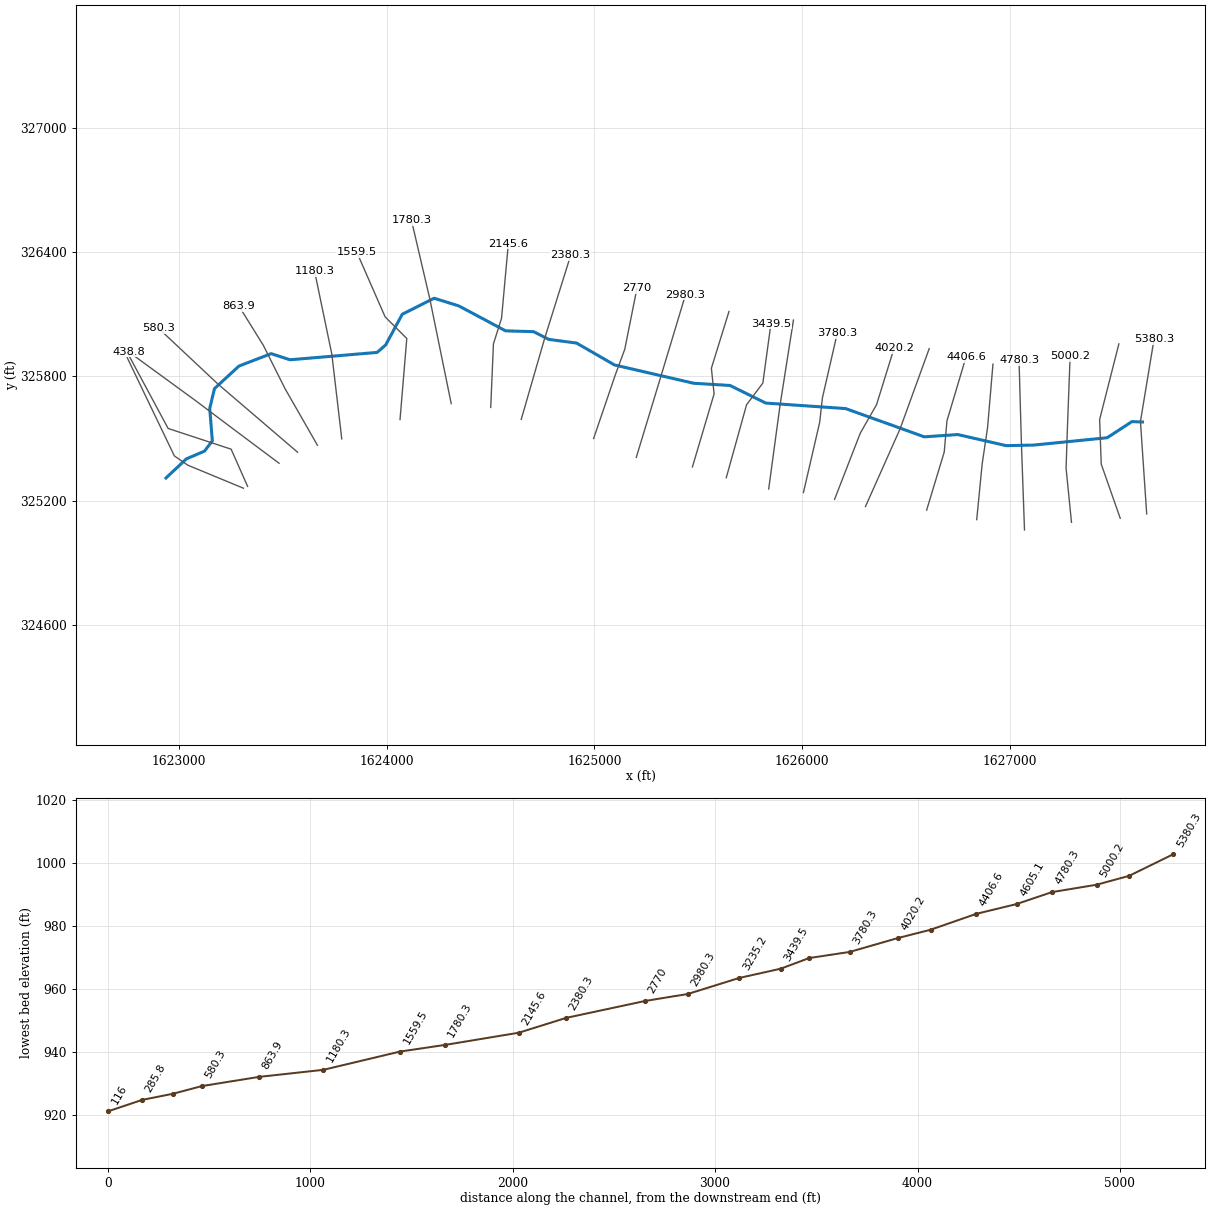
--- dngsstrcbr.prj (project) ---

Proj Title=dngsstrcbr
Current Plan=p01
Default Exp/Contr=0,0
English Units
Geom File=g01
Flow File=f01
Plan File=p01
BEGIN DESCRIPTION:
END DESCRIPTION:
DSS File=dss
DSS Export Rating Curves= 0
DSS Export Rating Curve Sorted= 0
DSS Export Volume Flow Curves= 0
DXF OffsetX= 0
DXF OffsetY= 0
DXF ScaleX= 0
DXF ScaleY= 0

--- dngsstrcbr.p01 (plan) ---

Plan Title=Approximate Study - 100 yr
Program Version=4.00
Short Identifier=100 yr
Geom File=g01
Flow File=f01
Subcritical Flow
K Sum by GR= 0
Std Step Tol= 0.01
Critical Tol= 0.01
Num of Std Step Trials= 20
Max Error Tol= 0.3
Flow Tol Ratio= 0.001
Split Flow NTrial= 30
Split Flow Tol= 0.02
Split Flow Ratio= 0.02
Log Output Level= 0
Friction Slope Method= 1
Unsteady Friction Slope Method= 2
Unsteady Bridges Friction Slope Method= 1
Parabolic Critical Depth
Global Vel Dist= 0 , 0 , 0
Global Log Level= 0
CheckData=True
Encroach Param=-1 ,0,0, 0
Run HTab= 0
Run UNet= 0
Run PostProcess= 0
Run WQNet= 0
UNET Theta= 0
UNET Theta Warmup= 0
UNET ZTol= 0
UNET ZSATol= 0
UNET MxIter= 0
UNET MaxInSteps= 0
UNET DtIC= 0
UNET DtMin= 0
UNET MaxCRTS= 0
UNET WFStab= 0
UNET SFStab= 0
UNET WFX= 1
UNET SFX= 1
UNET DSS MLevel= 1
UNET DZMax Abort= 0
UNET Convert EG Bridges= 0
UNET Use Existing IB Tables= 0
UNET Froude Reduction=False
UNET Froude Limit= 0
UNET Froude Power= 0
UNET Time Slicing=0,0, 5
DSS File=dss
Write IC File= 0
Echo Input=False
Echo Output=False
Write Detailed= 0
Detailed Automatic Start=False, 0
WQ ULTIMATE=-1
WQ Max Comp Step=1HOUR
WQ Output Interval=15MIN
WQ Output Selected Increments= 0
WQ Output face flow=0
WQ Output face velocity=0
WQ Output face area=0
WQ Output face dispersion=0
WQ Output cell volume=0
WQ Output cell surface area=0
WQ Output cell continuity=0
WQ Output face conc=0
WQ Output face dconc_dx=0
WQ Output face courant=0
WQ Output face peclet=0
WQ Output face adv mass=0
WQ Output face disp mass=0
WQ Output cell mass=0
WQ Output cell source sink temp=0
WQ Output cell source sink nsm=0
WQ Output MaxMinRange=-1
WQ Daily Max Min Mean=-1
WQ Daily Range=0
WQ Daily Time=0
WQ Create Restart=0
WQ Fixed Restart=0
WQ System Summary=False
Sorting and Armoring Iterations= 10
XS Update Threshold= 0.02
Hydraulics Update Threshold= 0.02
Energy Slope Method= 1
Volume Change Method= 0
XS Weighting Method= 0
Number of US Weighted Cross Sections= 1
Number of DS Weighted Cross Sections= 1
Upstream XS Weight=0.25
Main XS Weight=0.5
Downstream XS Weight=0.25
Number of DS XS's Weighted with US Boundary= 1
Upstream Boundary Weight= 1
Weight of XSs Associated with US Boundary= 0
Number of US XS's Weighted with DS Boundary= 1
Downstream Boundary Weight= 0.5
Weight of XSs Associated with DS Boundary= 0.5
Sediment Output Level= 4
Mass or Volume Output= 0
Output Increment Type= 1
Profile and TS Output Increment= 10
XS Output Flag= 0
XS Output Increment= 10
Disregard all LS=0
Disregard all Conn=0
Disregard all Breaches=0
Disregard all Pumps=0

--- dngsstrcbr.f01 (steady flow) ---

Flow Title=USGS Regression Equation
Program Version=4.00
Number of Profiles= 1
Profile Names=P100yr
River Rch & RM=dngsstrcbr,Main            ,5380.3
373.5043
River Rch & RM=dngsstrcbr,Main            ,3780.3
 394.287
River Rch & RM=dngsstrcbr,Main            ,1780.3
437.2999
River Rch & RM=dngsstrcbr,Main            ,1180.3
535.7979
River Rch & RM=dngsstrcbr,Main            ,285.8
563.4746
Boundary for River Rch & Prof#=dngsstrcbr,Main            , 1
Up Type= 0
Dn Type= 3
Dn Slope=0.011494
DSS Import GetInterval= 0
DSS Import GetPeak= 0
DSS Import FillOption= 0

--- dngsstrcbr.g01 (geometry) ---

Geom Title=USGS 3m DEM
Program Version=4.00

River Reach=dngsstrcbr      ,Main
Reach XY= 30
     1627638.589      325579.914     1627587.824      325581.842
     1627469.025      325504.178     1627116.646      325468.811
     1626983.123      325465.875     1626749.059      325519.413
     1626588.098      325508.467     1626209.465      325644.684
      1625824.98      325671.219     1625652.765      325756.084
     1625477.135      325766.943     1625096.299      325855.161
     1624913.854      325960.674     1624780.114      325978.326
     1624706.766      326015.714     1624572.076      326019.643
     1624346.428      326140.001     1624227.887      326176.874
     1624074.396       326099.61     1623994.596       325951.56
     1623953.105      325915.527      1623533.91       325880.09
     1623443.044       325909.65     1623288.178      325849.807
     1623170.372       325741.26     1623147.314      325645.408
     1623159.956      325489.146       1623122.4      325439.572
     1623034.926      325402.181     1622936.693      325309.928

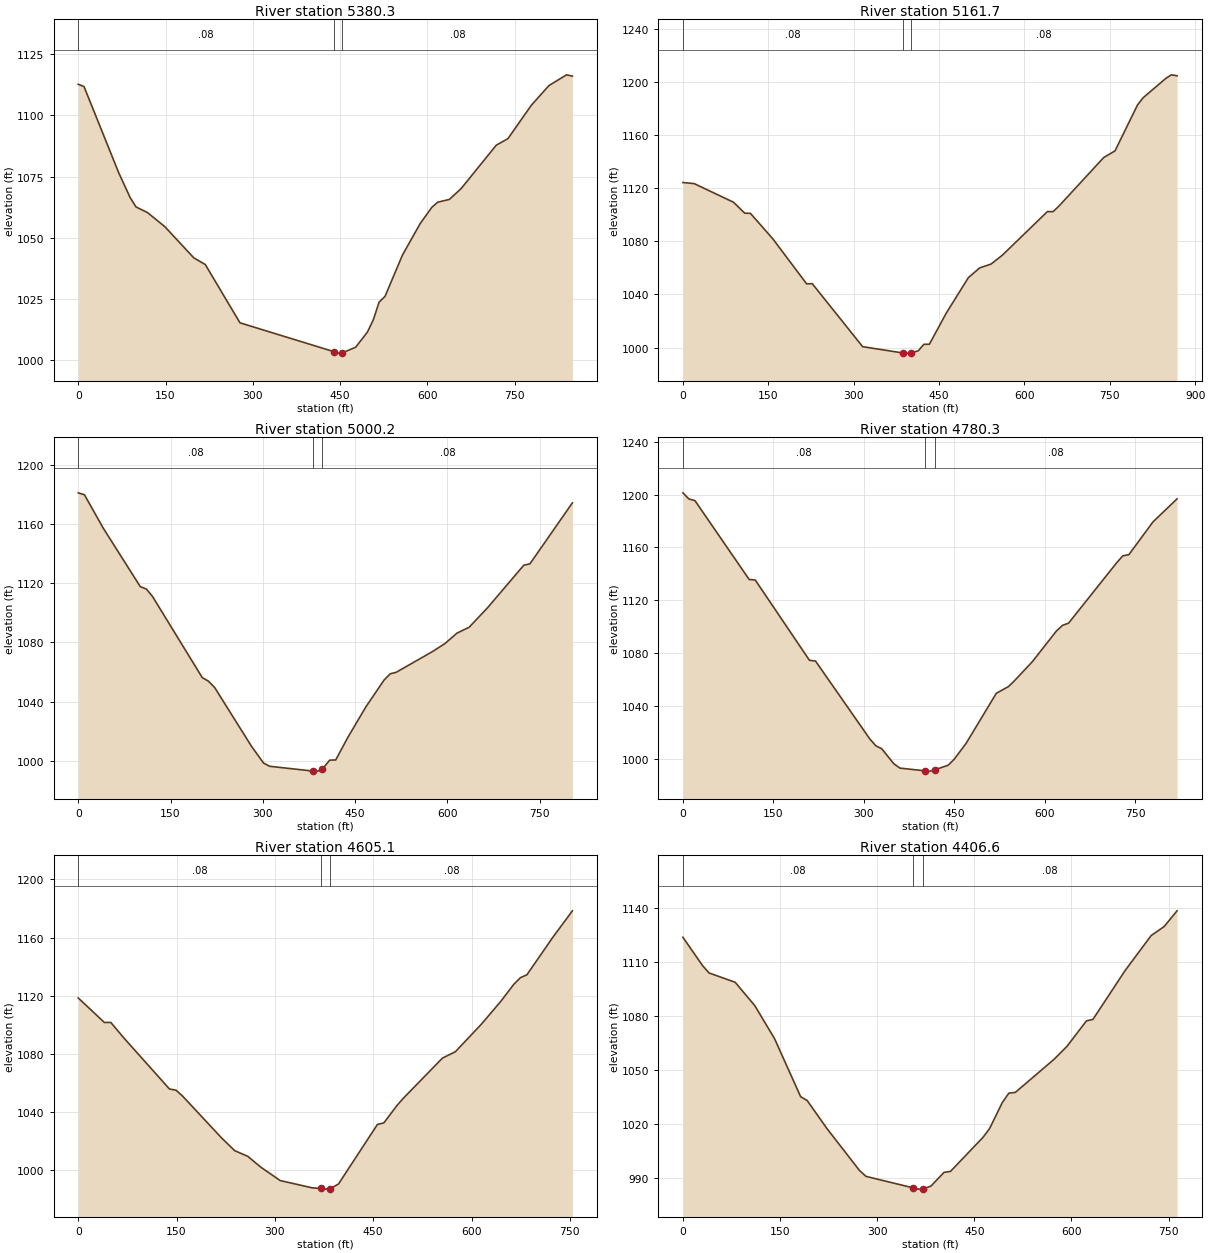
Type RM Length L Ch R = 1 ,5380.3  ,219.6,218.7,222.7
XS GIS Cut Line= 3
     1627659.026      325136.871     1627628.987      325582.602
     1627694.593      325979.972
#Sta/Elev= 30
       0 1112.75     9.9  1111.8    69.5 1076.59    89.3 1066.36    99.3 1062.57
   119.1 1060.25   148.9 1054.49   198.6 1041.75   218.4 1039.01     278 1015.17
   439.2 1003.39   446.7 1002.77   454.2  1002.9   476.9 1005.19   497.1 1011.38
   507.2 1016.39   517.2 1023.64   527.3 1025.96   557.5 1042.96   587.7 1055.72
   607.8  1062.4   617.9  1064.5     638 1065.64   658.2 1070.08   718.6 1087.82
   738.7 1090.51     779 1104.19   809.2 1112.22   839.4  1116.6   849.5 1116.05
#Mann= 3 , 0 , 0
       0     .08       0   439.2    .045       0   454.2     .08       0
Bank Sta=439.2,454.2
XS Rating Curve= 0 ,0
Exp/Cntr=0.3,0.1

Type RM Length L Ch R = 1 ,5161.7  ,162.8,161.4,160
XS GIS Cut Line= 4
     1627531.581      325115.743     1627440.171      325376.866
     1627432.436      325591.884     1627525.062      325956.643
#Sta/Elev= 30
       0 1124.22    19.8 1123.41    88.9  1109.4   108.7 1101.14   118.6 1101.05
   158.1 1081.81   217.4 1048.01   227.3 1048.12   315.8 1000.74   386.5     996
     394  995.88   401.5  996.09   413.6  997.65   423.4 1002.52   433.1 1002.56
   462.5 1025.83   501.7 1052.74   521.5 1060.01   541.3 1062.85   561.1 1069.49
   640.4 1102.35   650.3 1102.31   660.2 1106.27   739.4 1143.05   759.2 1148.02
   798.8 1182.62   808.7 1188.03   848.3 1202.49   858.2 1205.23   868.2 1204.52
#Mann= 3 , 0 , 0
       0     .08       0   386.5    .045       0   401.5     .08       0
Bank Sta=386.5,401.5
XS Rating Curve= 0 ,0
Exp/Cntr=0.3,0.1

Type RM Length L Ch R = 1 ,5000.2  ,218.5,219.9,221.2
XS GIS Cut Line= 4
     1627296.911      325096.187     1627270.837      325356.931
     1627277.355      325552.489     1627290.393      325897.975
#Sta/Elev= 30
       0  1180.9    10.1 1179.59    40.3 1157.28   100.8 1117.62   110.9 1115.91
   120.9 1110.84   201.6 1056.19   211.7 1053.75   221.7 1049.53   281.6 1009.85
   301.2  998.53     311  996.32   381.7  993.07   389.2  993.04   396.7  994.34
   408.8 1000.45   418.6 1000.58   438.1 1015.67   467.6  1036.4   497.2 1054.52
   507.1 1058.71     517 1059.77   576.2 1073.82     596  1079.1   615.8  1086.2
   635.5 1090.17   665.2 1103.21   724.4 1132.06   734.3 1132.95   803.4 1174.15
#Mann= 3 , 0 , 0
       0     .08       0   381.7    .045       0   396.7     .08       0
Bank Sta=381.7,396.7
XS Rating Curve= 0 ,0
Exp/Cntr=0.3,0.1

Type RM Length L Ch R = 1 ,4780.3  ,178.9,175.2,171.7
XS GIS Cut Line= 3
     1627070.644      325059.444     1627056.076      325468.832
     1627044.363      325878.076
#Sta/Elev= 30
       0 1201.33      10 1196.69      20 1195.42   109.9 1135.75   119.9 1135.36
   209.8 1074.59   219.8 1074.03   309.7 1015.16   319.7 1009.94   329.7  1007.6
   349.7  996.27   359.7     993   402.1   990.9   409.6  990.71   417.1  991.66
   439.6  995.15   449.6  999.64   469.6 1011.83   519.5 1049.61   539.5 1054.66
   549.4 1059.01   579.4 1073.62   619.3 1096.85   629.3 1101.04   639.3  1102.7
   719.2 1148.51   729.2 1153.65   739.2  1154.5   779.1 1179.28   819.1 1196.78
#Mann= 3 , 0 , 0
       0     .08       0   402.1    .045       0   417.1     .08       0
Bank Sta=402.1,417.1
XS Rating Curve= 0 ,0
Exp/Cntr=0.3,0.1

Type RM Length L Ch R = 1 ,4605.1  ,197.4,198.5,199.6
XS GIS Cut Line= 4
     1626840.609      325109.224     1626866.683      325376.487
     1626892.758      325552.489     1626918.832      325858.864
#Sta/Elev= 30
       0 1118.43    39.8 1101.59    49.7 1101.57    69.6 1090.91   139.2 1055.79
   149.2 1054.95   159.1 1050.95   218.8 1022.07   238.7 1013.36   258.6 1009.48
   278.4 1002.05   308.1   992.8   357.5  987.73   369.8  987.42   377.3   986.9
   384.8  987.31     397  990.42   456.4 1031.37   466.3  1032.5   486.1 1044.37
     496 1049.45   555.6 1077.03   575.4 1081.46   615.1 1100.41   644.8  1116.2
   664.7 1127.94   674.6 1132.37   684.5 1134.39   724.2 1160.29   753.9 1178.38
#Mann= 3 , 0 , 0
       0     .08       0   369.8    .045       0   384.8     .08       0
Bank Sta=369.8,384.8
XS Rating Curve= 0 ,0
Exp/Cntr=0.3,0.1

Type RM Length L Ch R = 1 ,4406.6  ,232.8,226.3,221.2
XS GIS Cut Line= 4
     1626599.421      325154.854     1626684.163      325435.154
       1626697.2      325585.082      1626788.46      325891.457
#Sta/Elev= 30
       0  1123.9    30.3 1108.16    40.4 1104.04    80.8 1098.83   111.1 1085.82
   141.4  1067.6   181.8 1035.23   191.9 1033.09   222.1 1017.66   272.6  994.21
   282.7   990.9   355.6   984.5   363.1   983.8   370.6  983.83   383.1  985.52
   403.2  993.12   413.2  993.67   463.3 1012.57   473.3 1017.32   493.3 1032.02
   503.3 1037.17   513.3  1037.6   573.2 1056.04   593.2 1063.28   623.1 1077.38
   633.1 1078.21   683.1 1105.52     723 1124.83     743 1129.83     763 1138.59
#Mann= 3 , 0 , 0
       0     .08       0   355.6    .045       0   370.6     .08       0
Bank Sta=355.6,370.6
XS Rating Curve= 0 ,0
Exp/Cntr=0.3,0.1

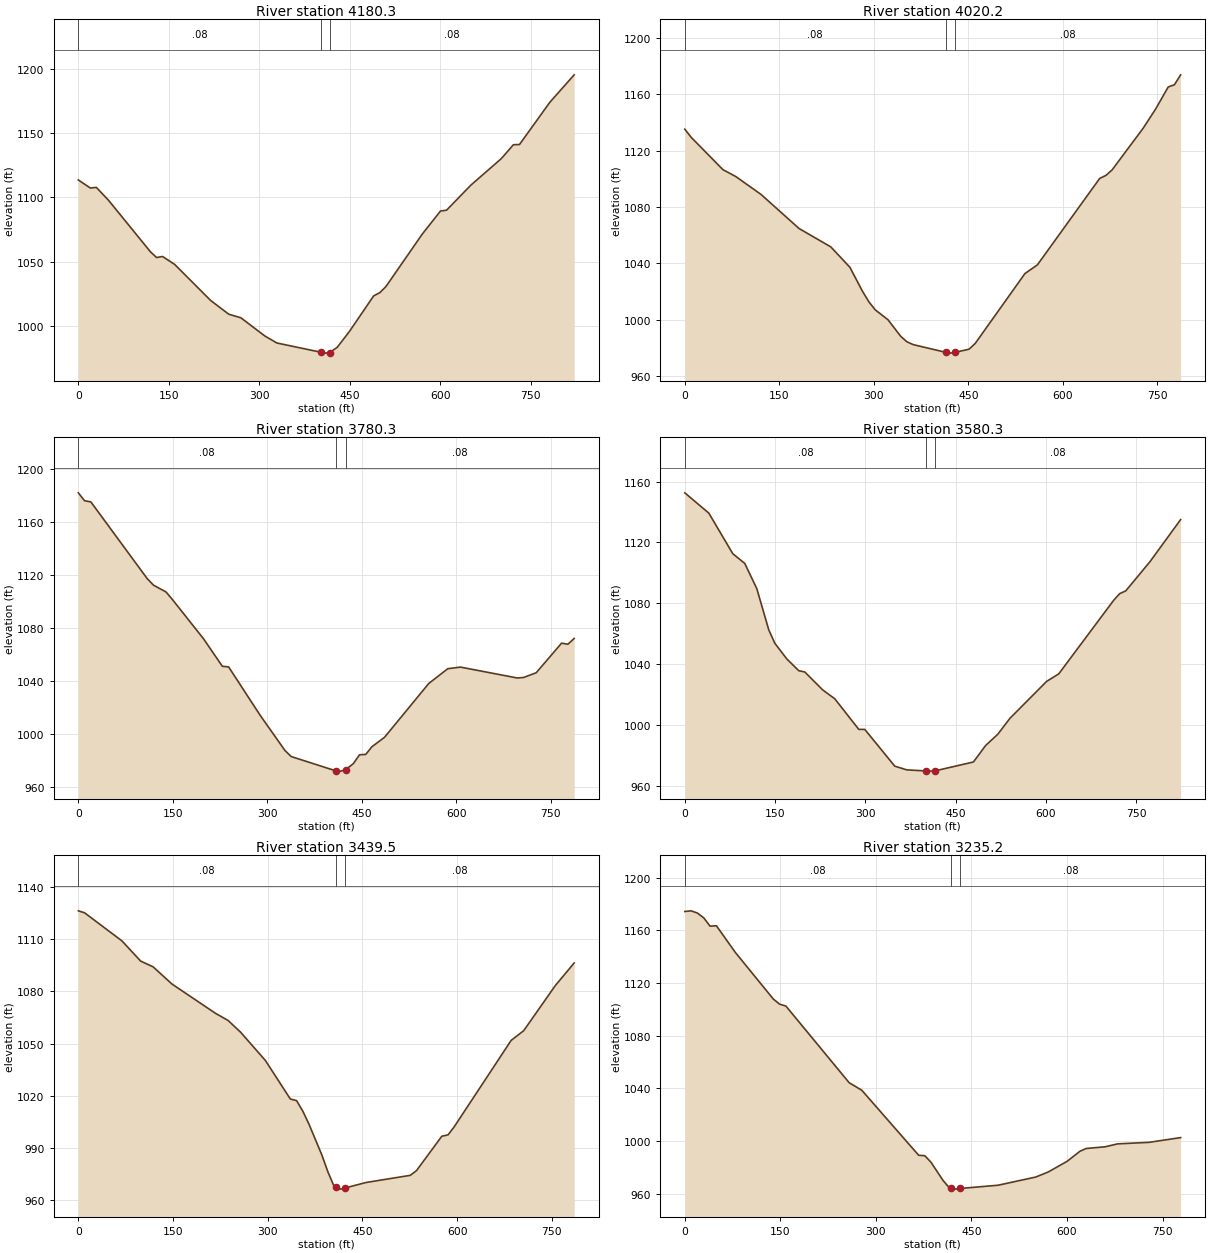
Type RM Length L Ch R = 1 ,4180.3  ,162.3,160.1,156.4
XS GIS Cut Line= 3
     1626304.877      325172.162     1626471.101      325545.782
     1626611.845      325933.782
#Sta/Elev= 30
       0 1113.61    19.9 1107.35    29.9  1107.8    49.9 1097.86   119.7 1057.55
   129.7  1053.2   139.6    1054   159.6 1047.86   219.4  1019.7   249.3 1009.06
   269.3 1006.28   309.2  992.07   329.1  986.62   401.4   979.5   408.9  978.74
   416.4  979.15   429.1  983.29   449.2  995.57   489.5 1023.35   499.5  1025.8
   509.6 1030.47     570 1071.45   600.2 1089.41   610.3 1090.08   650.5 1109.56
   700.9  1130.2     721 1141.05   731.1 1141.21   781.4  1174.1   821.7 1195.49
#Mann= 3 , 0 , 0
       0     .08       0   401.4    .045       0   416.4     .08       0
Bank Sta=401.4,416.4
XS Rating Curve= 0 ,0
Exp/Cntr=0.3,0.1

Type RM Length L Ch R = 1 ,4020.2  ,231.6,239.9,248.4
XS GIS Cut Line= 4
     1626156.156      325207.003     1626280.009      325526.415
     1626358.232      325663.306     1626442.974      325937.087
#Sta/Elev= 30
       0 1135.21    10.1 1129.44    60.5 1106.45    80.6 1101.65   120.9 1088.88
   181.4 1064.62   231.7 1051.58     262 1037.09   282.1 1019.96   292.2 1012.51
   302.3 1006.84   322.4  999.86   342.6  988.08   352.4   984.2   362.3  982.19
   413.9   976.7   421.4  976.12   428.9  976.67     451   978.9   460.8  982.97
   539.8 1032.67   559.5  1038.8   658.4 1100.23   668.3 1102.36   678.1 1106.29
   727.5 1135.97   747.3 1149.63   767.1 1165.19     777 1166.76   786.8 1173.81
#Mann= 3 , 0 , 0
       0     .08       0   413.9    .045       0   428.9     .08       0
Bank Sta=413.9,428.9
XS Rating Curve= 0 ,0
Exp/Cntr=0.3,0.1

Type RM Length L Ch R = 1 ,3780.3  ,200.4,199.9,199.1
XS GIS Cut Line= 4
     1626006.227      325239.596     1626084.451      325578.564
     1626097.488      325695.899     1626169.193      326008.792
#Sta/Elev= 30
       0 1182.15     9.9 1176.18    19.9 1175.28   109.3 1117.27   119.3 1112.31
   139.2 1107.18   149.1 1101.59   198.8 1071.69   228.6 1050.95   238.5 1050.52
   288.2 1014.17     328  987.25   337.9  982.69   409.2  971.81   416.7  971.68
   424.2  972.77   436.4  977.29   446.3  984.03   456.1  984.31   465.9  990.11
     486  997.29   556.2 1037.99   586.3 1049.12   606.4 1050.36   696.7 1042.11
   706.7  1042.5   726.7 1046.09   766.9 1068.45   776.9 1067.63   786.9    1072
#Mann= 3 , 0 , 0
       0     .08       0   409.2    .045       0   424.2     .08       0
Bank Sta=409.2,424.2
XS Rating Curve= 0 ,0
Exp/Cntr=0.3,0.1

Type RM Length L Ch R = 1 ,3580.3  ,151,140.8,131
XS GIS Cut Line= 3
     1625838.931      325256.874      1625893.68      325661.716
     1625958.143      326071.692
#Sta/Elev= 30
       0 1152.57    39.9 1139.24    79.7 1112.58    99.6  1106.2   119.6  1089.6
   139.5 1062.53   149.5 1053.77   169.4 1043.47   189.3  1035.7   199.3 1034.88
   229.2 1023.04   249.1 1017.28     289  997.15   298.9  997.16   348.7  973.02
   368.7  970.56     401  969.85   408.5  969.74     416  969.95   479.4  975.74
   499.6  986.55   519.9  993.99   540.1 1004.47   600.9 1028.68   621.1 1033.63
   712.2 1081.91   722.3 1086.34   732.4 1088.15   772.9 1107.49   823.5    1135
#Mann= 3 , 0 , 0
       0     .08       0     401    .045       0     416     .08       0
Bank Sta=401,416
XS Rating Curve= 0 ,0
Exp/Cntr=0.3,0.1

Type RM Length L Ch R = 1 ,3439.5  ,189.3,204.3,219.4
XS GIS Cut Line= 4
     1625634.667      325311.301     1625732.446      325663.306
     1625810.669      325767.603     1625849.781      326054.422
#Sta/Elev= 30
       0 1126.34     9.9 1125.21    69.1 1109.05    98.7 1097.45   118.5 1094.12
   148.1 1084.31   217.2 1067.42     237 1063.36   256.7 1056.67   296.2 1040.33
   335.7 1018.17   345.6 1017.24   355.5 1011.16   365.3 1003.67   385.4  986.22
   395.4  976.12   405.4  967.62     408   967.3   415.5  966.35     423  967.07
   455.6  970.16   525.7  974.28   535.6  977.02   575.6  996.75   585.5  997.55
   595.5 1002.31   685.4 1051.84   705.3 1057.44   755.2  1083.3   785.2 1096.36
#Mann= 3 , 0 , 0
       0     .08       0     408    .045       0     423     .08       0
Bank Sta=408,423
XS Rating Curve= 0 ,0
Exp/Cntr=0.3,0.1

Type RM Length L Ch R = 1 ,3235.2  ,262.9,254.9,246.9
XS GIS Cut Line= 4
     1625471.702       325363.45        1625576.      325715.455
     1625562.962      325839.308     1625647.704      326113.089
#Sta/Elev= 30
       0 1174.42     9.9 1174.92    19.8 1173.23    29.8 1169.54    39.7 1163.25
    49.6 1163.59    79.4 1143.27   138.9 1107.91   148.8    1104   158.8  1102.5
     258  1044.3   277.8 1038.59   367.1  989.17   376.7  988.82   386.3  983.96
   405.5  969.93     415  964.58   417.1  964.32   424.6  963.42   432.1  963.92
   491.7  966.38     551  972.61   570.7   976.5   600.4  984.63   620.1  992.13
     630   994.3   659.7  995.59   679.4  997.81   728.9  998.98   778.3 1002.58
#Mann= 3 , 0 , 0
       0     .08       0   417.1    .045       0   432.1     .08       0
Bank Sta=417.1,432.1
XS Rating Curve= 0 ,0
Exp/Cntr=0.3,0.1

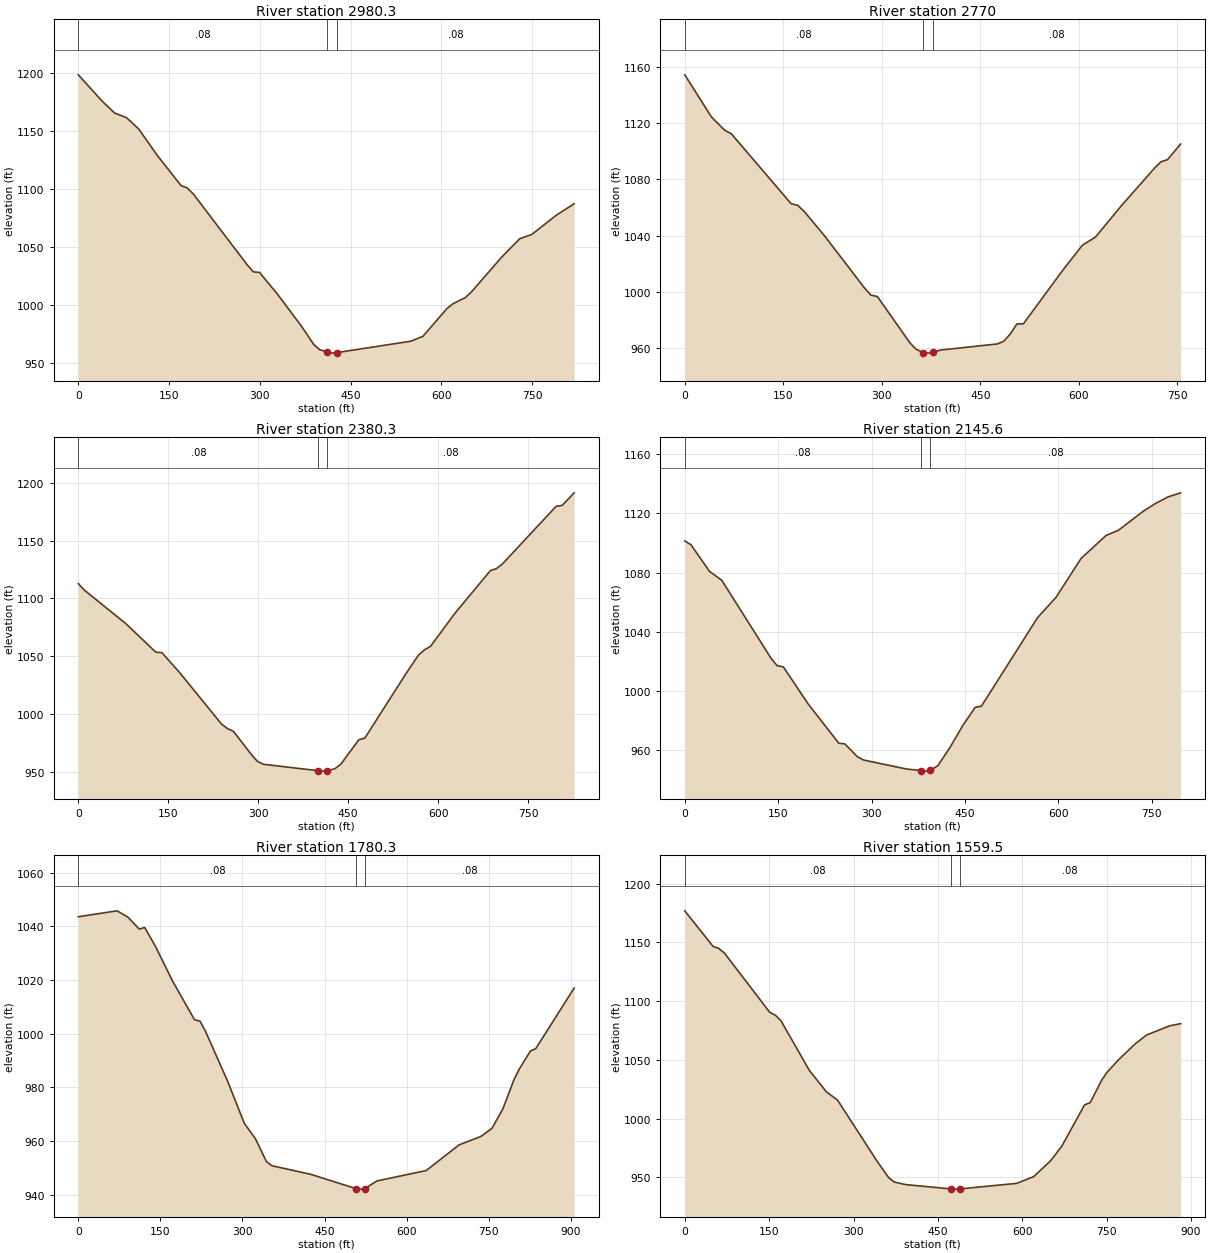
Type RM Length L Ch R = 1 ,2980.3  ,211.5,210.3,209.1
XS GIS Cut Line= 3
     1625201.272      325409.242     1625320.093      325800.944
     1625438.364      326193.844
#Sta/Elev= 30
       0 1198.53    39.9 1175.55    59.9 1165.59    79.9 1161.48    99.8 1151.79
   129.8 1129.49   169.7    1103   179.7 1100.94   189.7 1095.95   279.5  1034.3
   289.5 1028.43   299.5 1027.99   329.5 1009.02   369.4  981.13   389.4  965.59
   399.3   961.2   411.8  959.32   419.3  958.31   426.8  958.73   549.4  968.57
   569.5  972.76   609.5  996.88   619.5 1000.99   639.5 1006.19   649.5 1010.97
   699.6 1041.06   729.6 1057.03   749.6 1060.76   789.6 1077.17   819.6 1087.28
#Mann= 3 , 0 , 0
       0     .08       0   411.8    .045       0   426.8     .08       0
Bank Sta=411.8,426.8
XS Rating Curve= 0 ,0
Exp/Cntr=0.3,0.1

Type RM Length L Ch R = 1 ,2770    ,388.2,389.7,390.7
XS GIS Cut Line= 4
     1624995.844      325500.341     1625100.141      325806.715
     1625145.772      325930.568     1625204.439      326223.906
#Sta/Elev= 30
       0 1154.66    40.5 1124.64    60.7 1115.11    70.8 1112.64   161.8 1062.73
   171.9 1061.54     182 1057.08   212.4 1039.99   273.1 1002.85   283.2  997.58
   293.3  996.41   342.5  963.56   351.9  958.93   363.3  956.44   370.8   956.1
   378.3  956.82   389.6   958.3   475.6  962.64   485.5  964.52   495.5  969.76
   505.5   976.9   515.5  977.03   575.3 1015.17   605.2 1033.05   625.1 1038.86
     665 1061.45   714.9 1088.01   724.9 1092.64   734.8 1094.13   754.8 1105.29
#Mann= 3 , 0 , 0
       0     .08       0   363.3    .045       0   378.3     .08       0
Bank Sta=363.3,378.3
XS Rating Curve= 0 ,0
Exp/Cntr=0.3,0.1

Type RM Length L Ch R = 1 ,2380.3  ,235.2,234.8,234.7
XS GIS Cut Line= 3
     1624647.231      325592.196     1624760.325      325984.037
     1624885.401      326383.863
#Sta/Elev= 30
       0  1112.8     9.9 1107.23    79.6 1078.04   129.3 1053.48   139.3 1053.16
   169.1 1035.81   238.7  991.43   248.7  987.48   258.6  985.15   288.5  965.12
   298.4  959.31   308.4  956.68   400.3  951.07   407.8  950.73   415.3  951.09
   427.8  952.83   437.8  956.75   467.7  977.83   477.7  979.24   547.5  1035.9
   567.4 1051.13   577.4  1055.6   587.4 1058.65   627.3 1086.71   687.1 1124.04
   697.1 1125.74   707.1 1129.75   796.8 1179.63   806.8 1180.36   826.8 1191.26
#Mann= 3 , 0 , 0
       0     .08       0   400.3    .045       0   415.3     .08       0
Bank Sta=400.3,415.3
XS Rating Curve= 0 ,0
Exp/Cntr=0.3,0.1

Type RM Length L Ch R = 1 ,2145.6  ,355,365.2,376.1
XS GIS Cut Line= 4
      1624500.43      325650.268     1624513.467      325956.643
     1624552.579      326080.496     1624585.172       326439.02
#Sta/Elev= 30
       0 1101.43     9.9 1098.89    39.6 1080.95    59.4 1074.88   138.5 1022.27
   148.4  1017.2   158.3 1016.42   197.8  991.59   247.3  964.87   257.2  964.35
     277  955.85   286.9  953.52   356.6   947.4   379.1  946.42   386.6     946
   394.1  946.44   406.6   949.7   426.5  962.32   446.5  976.77   466.5  989.06
   476.5  989.85   566.5 1049.54   596.5 1063.47   636.5 1089.57   676.5 1105.11
   696.5 1108.65   736.5 1121.51   756.5 1126.84   776.5 1131.22   796.5 1133.95
#Mann= 3 , 0 , 0
       0     .08       0   379.1    .045       0   394.1     .08       0
Bank Sta=379.1,394.1
XS Rating Curve= 0 ,0
Exp/Cntr=0.3,0.1

Type RM Length L Ch R = 1 ,1780.3  ,209.2,220.9,232
XS GIS Cut Line= 3
      1624310.21      325668.428     1624207.187      326173.588
     1624118.475      326554.053
#Sta/Elev= 30
       0 1043.55    70.8 1045.75      91 1043.34   111.2 1038.97   121.3 1039.53
   141.5 1032.31   171.9 1019.73   212.3  1005.2   222.4 1004.67   232.5 1000.85
   272.9  982.28   303.3  966.64   323.5  960.97   343.7  952.41   353.8  950.83
   424.6  947.65   508.1  942.27   515.6  942.12   523.1  942.25   545.6  945.15
   635.8  949.04   695.9   958.6   735.9  961.75     756  964.76     776  972.03
     796  982.77   806.1  986.91   826.1   993.5   836.1  994.45   906.2 1016.98
#Mann= 3 , 0 , 0
       0     .08       0   508.1    .045       0   523.1     .08       0
Bank Sta=508.1,523.1
XS Rating Curve= 0 ,0
Exp/Cntr=0.3,0.1

Type RM Length L Ch R = 1 ,1559.5  ,392.7,379.1,367.3
XS GIS Cut Line= 4
     1624063.683      325591.601     1624096.276      325982.717
     1623991.979      326087.015     1623855.088      326399.908
#Sta/Elev= 30
       0 1176.86    50.3 1146.55    60.4 1144.89    70.4 1140.95     151 1090.52
     161    1088   171.1 1083.22   221.4  1041.1   251.6 1022.91   271.7 1015.69
   342.2  963.53   362.3  949.91   372.3  946.07   392.5  943.88   473.5  940.21
     481  940.02   488.5  940.19   590.2  944.94   620.3  950.66   650.5  964.21
   670.6  976.83   710.7 1011.71   720.8 1013.64   740.9 1032.52   750.9 1039.57
     771 1050.02   801.1 1063.81   821.2 1071.22   861.4  1078.9   881.5 1080.88
#Mann= 3 , 0 , 0
       0     .08       0   473.5    .045       0   488.5     .08       0
Bank Sta=473.5,488.5
XS Rating Curve= 0 ,0
Exp/Cntr=0.3,0.1

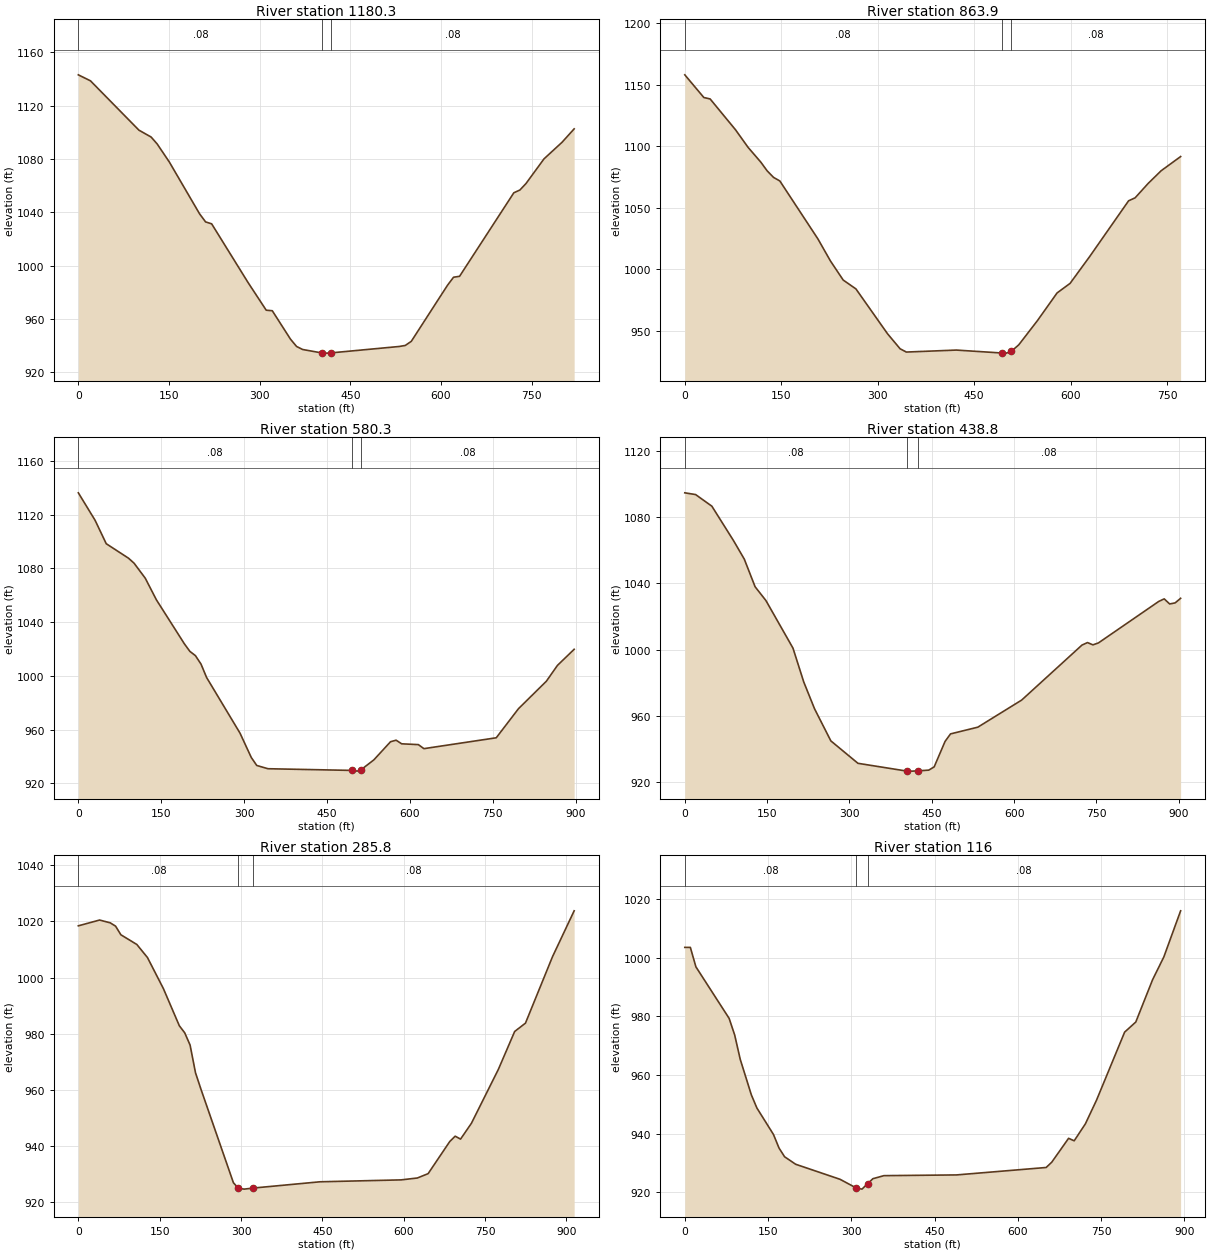
Type RM Length L Ch R = 1 ,1180.3  ,309.5,316.5,321.7
XS GIS Cut Line= 3
      1623783.12      325498.618     1623735.331      325907.028
     1623652.156      326307.686
#Sta/Elev= 30
       0 1143.19    20.1 1138.68   100.3 1101.63   120.4 1096.49   130.4 1091.31
   150.4 1077.85   200.6 1038.83   210.6 1032.74   220.6  1031.3   280.8  987.24
   310.9  966.43   320.9  966.05     351  944.73   361.1  939.21   371.1  936.94
   403.7  934.29   411.2  934.21   418.7  934.42     531   939.2   540.9  939.96
   550.9  943.05   610.8  985.15   620.8  991.19   630.8   991.9   720.6 1054.62
   730.6 1056.68   740.6  1061.5   770.5 1080.07   800.4 1092.56   820.4 1102.61
#Mann= 3 , 0 , 0
       0     .08       0   403.7    .045       0   418.7     .08       0
Bank Sta=403.7,418.7
XS Rating Curve= 0 ,0
Exp/Cntr=0.3,0.1

Type RM Length L Ch R = 1 ,863.9   ,275.7,283.5,290.4
XS GIS Cut Line= 4
     1623666.048      325467.748     1623509.602      325741.529
     1623405.304      325950.124      1623287.97      326139.164
#Sta/Elev= 30
       0 1158.12    29.6 1139.69    39.4 1138.52    78.8 1113.51    98.5 1099.12
   118.2 1087.18   128.1 1080.08     138 1074.78   147.8 1071.87   206.9 1024.86
   226.6 1006.78   246.3  991.36   266.1  984.16   315.3  947.68   334.8  935.51
   344.5  932.85   422.2  934.46   492.5  932.09     500  931.98   507.5  933.32
   519.4  938.77   548.5   958.5   578.9  980.89   599.1  988.64   629.5  1010.4
   690.1 1055.76   700.2 1058.15   720.5 1069.85   740.7 1080.17     771  1091.7
#Mann= 3 , 0 , 0
       0     .08       0   492.5    .045       0   507.5     .08       0
Bank Sta=492.5,507.5
XS Rating Curve= 0 ,0
Exp/Cntr=0.3,0.1

Type RM Length L Ch R = 1 ,580.3   ,144.1,141.5,140.1
XS GIS Cut Line= 3
     1623570.373      325434.285      1623187.31      325762.745
      1622901.14      326031.695
#Sta/Elev= 30
       0  1136.3    30.3 1115.87    50.5 1098.41    90.8 1087.62   100.9 1083.89
   121.1 1072.74   141.3 1056.61   191.7 1023.99   201.8 1018.26   211.9 1015.05
     222 1008.78   232.1   998.8   292.7  957.27   312.9  939.27   322.9  933.27
   343.1  930.84   494.5  929.58   504.6  929.05   512.1  930.24   534.8  937.42
     565  950.94   575.1  952.08   585.2  949.39   615.4  948.79   625.4  945.79
   756.3  953.88   796.6  975.57     847     996   867.1  1007.8   897.3 1019.78
#Mann= 3 , 0 , 0
       0     .08       0   494.5    .045       0   512.1     .08       0
Bank Sta=494.5,512.1
XS Rating Curve= 0 ,0
Exp/Cntr=0.3,0.1

Type RM Length L Ch R = 1 ,438.8   ,142.5,153,163.2
XS GIS Cut Line= 4
     1623481.379      325380.914     1623252.697      325552.306
     1623078.409      325683.603     1622755.885      325919.234
#Sta/Elev= 30
       0 1094.68    19.7 1093.63    49.3 1086.62    88.7 1065.86   108.4 1054.65
   128.1 1037.96   147.8 1029.64   197.1 1000.91   216.8   980.4   236.5   964.2
   266.1   944.9   315.5  931.35   404.7  926.64   414.7  926.63   424.7  926.78
   444.5  927.23   454.4  929.21   474.2  944.57   484.2  949.11   533.9  953.17
   613.8  969.54   723.7 1002.75   733.7 1004.26   743.6 1002.88   753.6 1004.03
   863.5 1029.09   873.5 1030.65   883.4 1027.57   893.4 1028.21   903.4 1030.99
#Mann= 3 , 0 , 0
       0     .08       0   404.7    .045       0   424.7     .08       0
Bank Sta=404.7,424.7
XS Rating Curve= 0 ,0
Exp/Cntr=0.3,0.1

Type RM Length L Ch R = 1 ,285.8   ,175.7,169.9,164
XS GIS Cut Line= 4
     1623329.783      325269.538     1623250.373      325448.895
     1622947.112       325548.82     1622758.408      325900.279
#Sta/Elev= 30
       0 1018.41    39.2 1020.47    58.8 1019.48    68.7 1018.29    78.5 1015.22
   107.9 1011.77   127.5 1007.12   156.9  996.05   186.3  982.82   196.2  980.32
   206.1  975.97   216.1  966.08   226.1  960.26     286  926.95  295.22  924.96
  305.95  924.67  321.85  925.04   445.6  927.28   595.2  927.96   625.2  928.63
   645.1  930.18     685  941.62     695  943.52   704.9  942.48   724.9   948.1
   774.7  967.33   804.7   980.8   824.6  983.76   874.5 1007.43   914.4 1023.75
#Mann= 3 , 0 , 0
       0     .08       0  295.22    .045       0  321.85     .08       0
Bank Sta=295.22,321.85
XS Rating Curve= 0 ,0
Exp/Cntr=0.3,0.1

Type RM Length L Ch R = 1 ,116     ,119.3,116,112.6
XS GIS Cut Line= 4
     1623309.631      325260.664     1623042.061      325371.633
     1622977.091      325416.493     1622750.275      325889.822
#Sta/Elev= 30
       0 1003.56      10 1003.56      20  996.92    79.9  979.31    89.9  973.63
    99.9  965.34   119.9  953.22   129.9  948.72   159.8  939.67   169.8  935.05
   179.8  932.07   199.8   929.5   279.7  924.37   309.3  921.37   319.3  921.01
   329.3  922.84     339  924.57   358.8  925.61   489.7  925.86   651.2   928.4
   661.3  930.21   691.6  938.36   701.7  937.51   721.9  943.31   742.1  951.45
   792.6  974.62   812.7  978.07     843  992.52   863.2 1000.27   893.5 1016.04
#Mann= 3 , 0 , 0
       0     .08       0   309.3    .045       0   329.3     .08       0
Bank Sta=309.3,329.3
XS Rating Curve= 0 ,0
Exp/Cntr=0.3,0.1
Stream Node=dngsstrcbr      ,Main            , 0 , 0 ,Upstream end
Stream Node=dngsstrcbr      ,Main            , 0 , 1 ,Downstream end

Chan Stop Cuts=-1
Use User Specified Reach Order=0